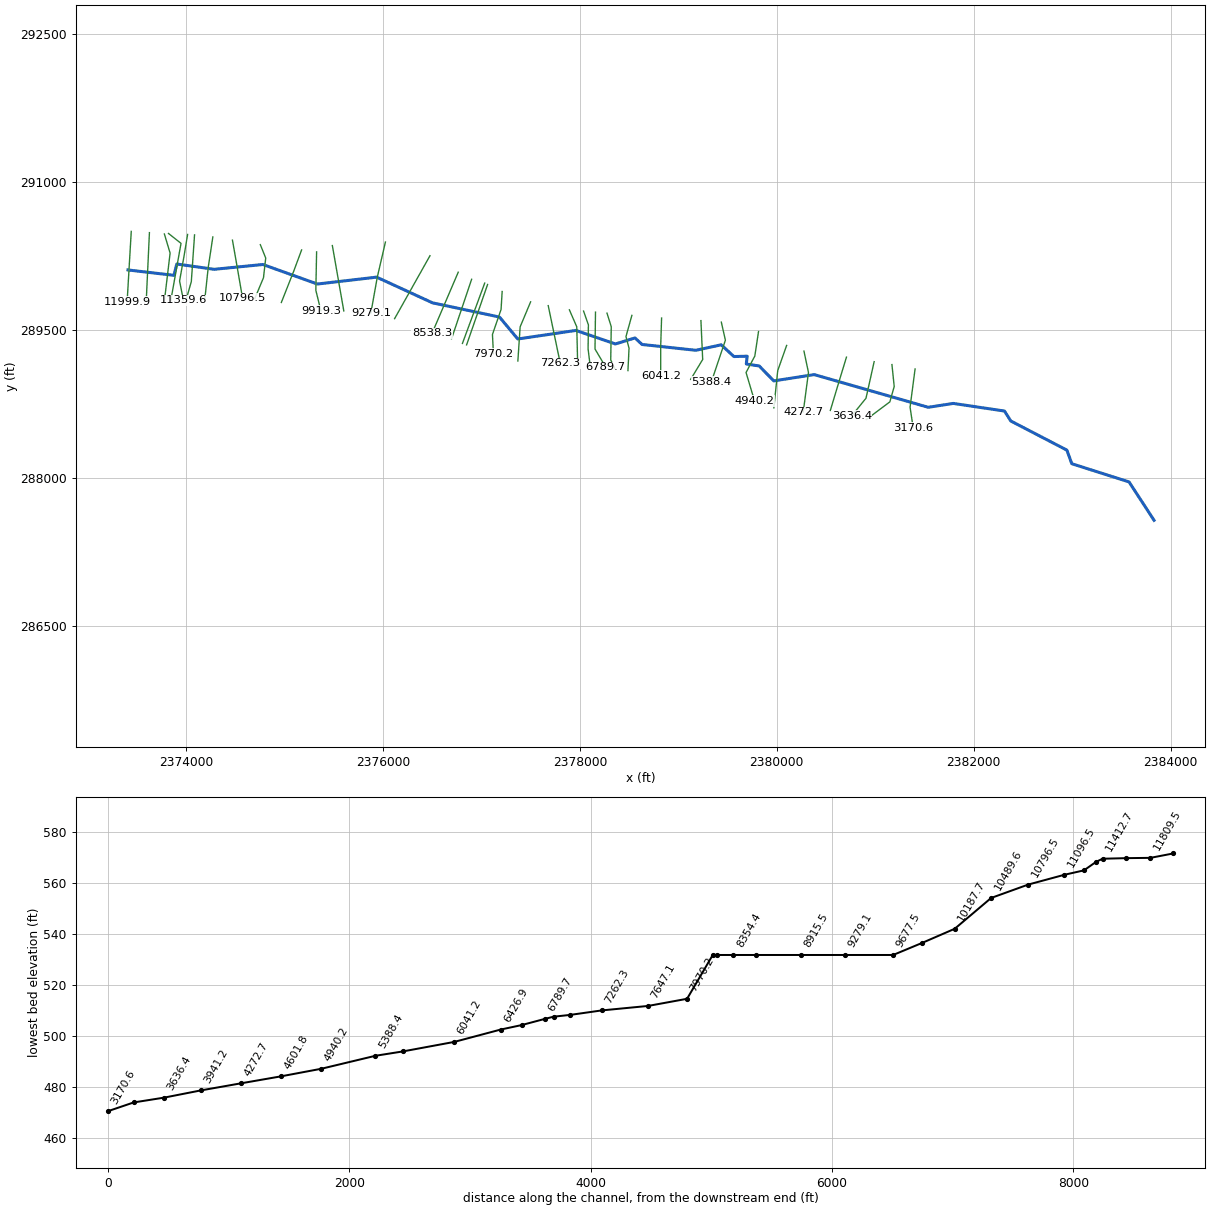
--- DUNCANRUN.prj (project) ---

Proj Title=DUNCANRUN
Current Plan=p01
Default Exp/Contr=0,0
English Units
Geom File=g01
Flow File=f01
Plan File=p01
BEGIN DESCRIPTION:
END DESCRIPTION:
DSS Export Rating Curves= 0
DSS Export Rating Curve Sorted= 0
DSS Export Volume Flow Curves= 0
DXF OffsetX= 0
DXF OffsetY= 0
DXF ScaleX= 0
DXF ScaleY= 0

--- DUNCANRUN.p01 (plan) ---

Plan Title=Floodplain
Program Version=4.00
Geom File=g01
Flow File=f01
K Sum by GR=0
Std Step Tol=0.01
Critical Tol=0.01
Num of Std Step Trials=20
Max Error Tol=0.3
Flow Tol Ratio=0.001
Split Flow NTrial=30
Split Flow Tol=0.02
Split Flow Ratio=0.02
Log Output Level=0
Friction Slope Method=1
Unsteady Friction Slope Method=2
Unsteady Bridges Friction Slope Method=1
Global Log Level=0
CheckData=False
Run HTab=0
Run UNet=0
Run PostProcess=0
UNET Theta=0
UNET Theta Warmup=0
UNET ZTol=0
UNET ZSATol=0
UNET MxIter=0
UNET MaxInSteps=0
UNET DtIC=0
UNET DtMin=0
UNET MaxCRTS=0
UNET WFStab=0
UNET SFStab=0
UNET WFX=0
UNET SFX=0
UNET DSS MLevel=0
UNET DZMax Abort=0
UNET Convert EG Bridges=0
UNET Use Existing IB Tables=0
UNET Froude Limit=0
UNET Froude Power=0
Write IC File=0
Echo Input=False
Echo Output=False
Write Detailed=0

--- DUNCANRUN.f01 (steady flow) ---

Flow Title=NFF Regression Equation
Program Version=4.00
Number of Profiles=1
Profile Names=P100yr
River Rch & RM=DUNCANRUN,Main      ,11999.9
970.5287
River Rch & RM=DUNCANRUN,Main      ,10489.6
988.2392
River Rch & RM=DUNCANRUN,Main      ,5388.4
1092.051
River Rch & RM=DUNCANRUN,Main      ,367.3
1198.847
River Rch & RM=DUNCANRUN,Main      ,21
1199.445
Boundary for River Rch & Prof#=DUNCANRUN,Main      ,1
Up Type=0
Dn Type=3
Dn Slope=0.007633

--- DUNCANRUN.g01 (geometry) ---

Geom Title=USGS 10m DEM
Program Version=4.10

River Reach=DUNCANRUN       ,Main
Reach XY= 30
     2373410.784      290106.619     2373877.363      290052.365
     2373906.293      290166.893     2374285.349      290113.129
     2374780.575      290162.066     2375334.373      289964.152
     2375936.044      290033.941     2376503.752      289773.524
     2377184.308      289629.427     2377370.072      289407.205
     2377960.349      289494.011     2378361.391      289356.858
     2378560.475      289417.762     2378632.225      289351.649
     2379179.099      289292.622     2379436.044      289348.177
     2379565.384      289229.254     2379699.933      289232.726
     2379691.252      289153.733     2379822.328      289133.768
     2379969.898      288982.552     2380381.356      289046.354
     2381538.894      288715.126     2381793.885      288754.188
     2382313.634      288677.148     2382377.653      288576.237
     2382947.314      288281.098     2382997.227      288143.294
     2383578.825      287958.833     2383832.986      287569.899

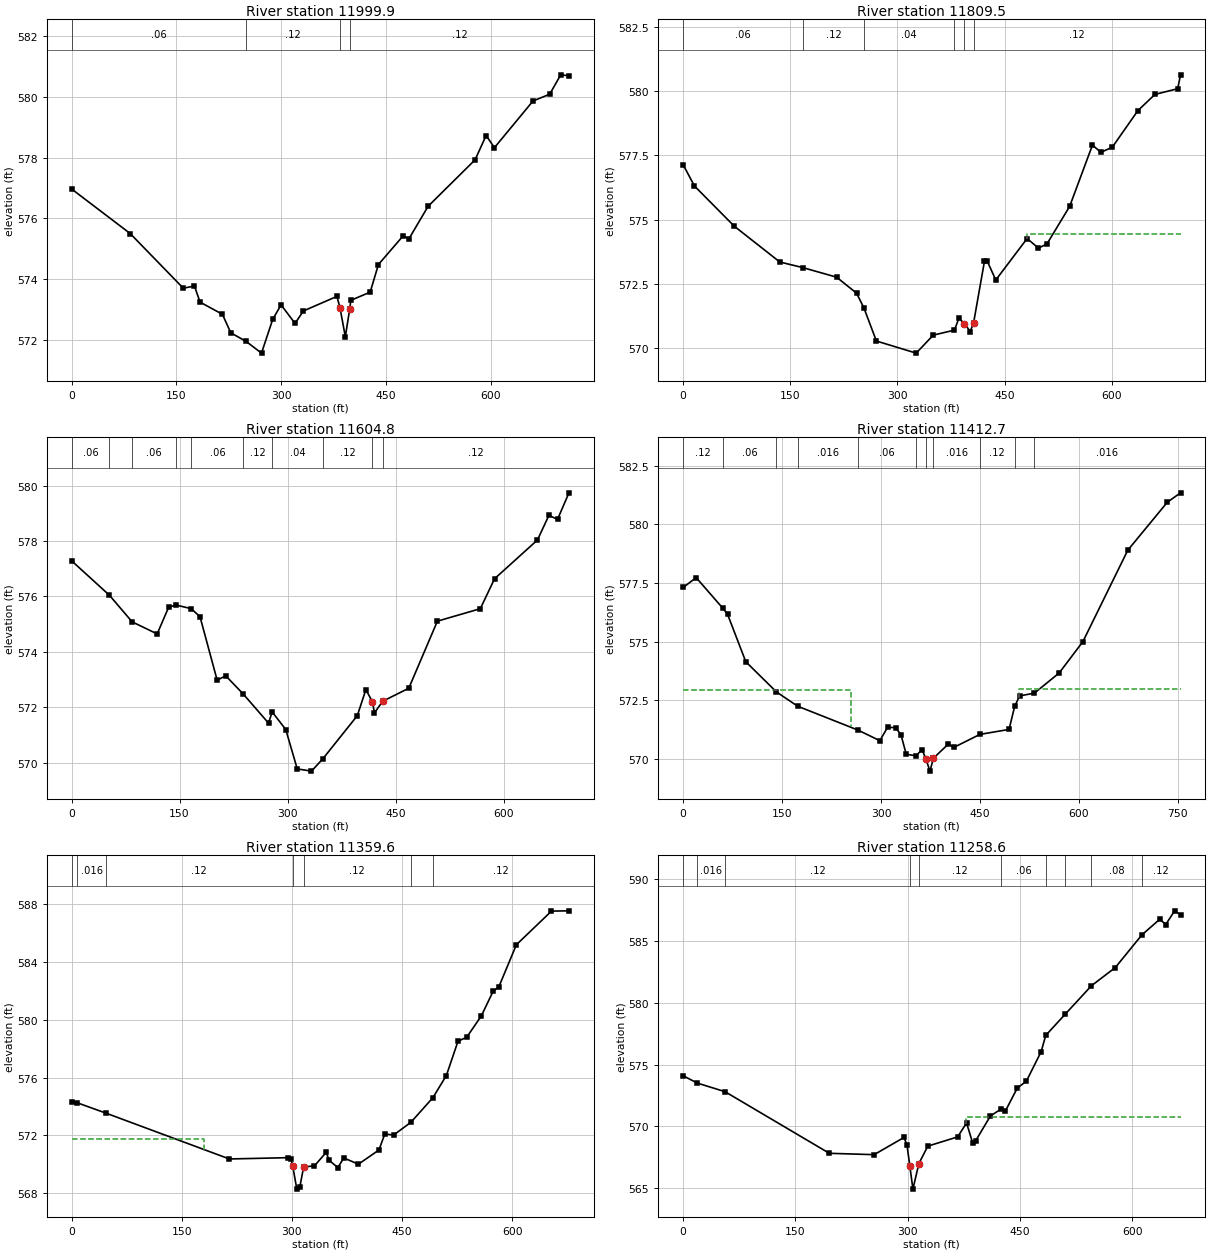
Type RM Length L Ch R = 1 ,11999.9 ,190.2,190.5,190.8
XS GIS Cut Line= 3
     2373443.785      290497.353     2373420.766      290106.032
     2373401.961      289786.332
#Sta/Elev= 30
       0  576.97      84   575.5     160   573.7     176  573.77     184  573.24
     216  572.84     228  572.23  250.02571.9447     272  571.56     288  572.67
     300  573.15     320  572.54     332  572.95     380  573.43   384.5  573.04
     392   572.1  398.42  573.03   399.9   573.3   427.6  573.57   439.4  574.48
     475  575.43   482.9  575.32   510.6   576.4   577.8  577.93   593.6  578.73
   605.5  578.33   660.8  579.87   684.6  580.09   700.4  580.73   712.2   580.7
#Mann= 4 ,-1 , 0
       0     .06       0  250.02     .12       0   384.5    .045       0
  398.42     .12       0
Bank Sta=384.5,398.42
XS Rating Curve= 0 ,0
Exp/Cntr=0.3,0.1

Type RM Length L Ch R = 1 ,11809.5 ,206.4,204.7,203.1
XS GIS Cut Line= 2
     2373628.398      290484.974     2373595.879      289789.542
#Sta/Elev= 30
       0  577.14    15.9  576.31    71.6  574.75   135.3  573.36  167.63573.1412
   214.8  572.77   242.7  572.15  253.04571.5763   270.5  570.29   326.2  569.82
   350.1  570.52  379.73570.7136   385.9  571.17   393.8  570.97   401.8  570.66
   406.5  570.99   421.7  573.38   425.7  573.39   437.6  572.66   481.4  574.27
   497.3   573.9   509.2  574.06     541  575.52   572.9   577.9   584.8  577.62
   600.7  577.82   636.5  579.24   660.4  579.87   692.2  580.09   696.2  580.63
#Mann= 6 ,-1 , 0
       0     .06       0  167.63     .12       0  253.04     .04       0
  379.73     .12       0   393.8    .045       0   406.5     .12       0
#XS Ineff= 2 , 0
                          481.84          574.43
Permanent Ineff=
       F       F
Bank Sta=393.8,406.5
XS Rating Curve= 0 ,0
Exp/Cntr=0.3,0.1

Type RM Length L Ch R = 1 ,11604.8 ,194.9,192.1,78.7
XS GIS Cut Line= 3
     2373780.172      290471.294     2373838.329      290277.679
     2373780.441      289792.597
#Sta/Elev= 30
       0  577.29   52.67576.0437   84.14575.0853   118.9  574.65   134.8  575.61
  144.91575.6934   166.2575.5607   178.4  575.27   202.2  572.98   214.1  573.14
  238.76 572.472   273.6  571.43  278.53571.8388   297.5   571.2   313.4  569.78
   333.2   569.7  349.06570.1479   396.8   571.7   408.7  572.64  417.86   572.2
   420.6   571.8     432  572.22   468.3  572.69     508  575.11   567.6  575.56
   587.4  576.64     647  578.04   662.9  578.93   674.8  578.78   690.7  579.74
#Mann= 10 ,-1 , 0
       0     .06       0   52.67     .12       0   84.14     .06       0
  144.91     .08       0   166.2     .06       0  238.76     .12       0
  278.53     .04       0  349.06     .12       0  417.86    .045       0
     432     .12       0
Bank Sta=417.86,432
XS Rating Curve= 0 ,0
Exp/Cntr=0.3,0.1

Type RM Length L Ch R = 1 ,11412.7 ,53.2,53.1,159.2
XS GIS Cut Line= 3
     2373821.899      290476.738     2373949.247      290376.195
     2373844.894      289793.664
#Sta/Elev= 30
       0  577.31    19.8  577.73   60.09576.4258    67.3  576.17      95  574.14
  141.46572.8508  173.68572.2408  265.53571.2167   298.2  570.77   310.2  571.35
   322.2  571.32   330.2  571.03   338.2  570.19  353.09570.1251   362.2  570.39
   367.9     570   374.2  569.47  379.42  570.02   402.2  570.63   410.2  570.48
   449.9571.0377   494.1  571.25  502.59572.2292   510.1  572.68  532.49572.7997
   570.1  573.66   606.1     575   674.1   578.9   734.1  580.95   754.1  581.35
#Mann= 11 ,-1 , 0
       0     .12       0   60.09     .06       0  141.46     .08       0
  173.68    .016       0  265.53     .06       0  353.09    .016       0
   367.9    .045       0  379.42    .016       0   449.9     .12       0
  502.59     .08       0  532.49    .016       0
#XS Ineff= 2 , 0
          255.11  572.92  508.57          572.97
Permanent Ineff=
       F       F
Bank Sta=367.9,379.42
XS Rating Curve= 0 ,0
Exp/Cntr=0.3,0.1

Type RM Length L Ch R = 1 ,11359.6 ,98.4,101,103.3
XS GIS Cut Line= 4
     2374016.144      290466.147     2373979.737       290246.18
     2373934.521      289994.653     2373973.695       289799.63
#Sta/Elev= 30
       0  574.34    7.88574.2536   46.86 573.537     215  570.36   294.8  570.45
   298.8  570.36   301.1   569.9   306.8  568.27   310.8  568.39   316.1  569.81
   330.8  569.88   346.8  570.82   350.7  570.27   362.7  569.76   370.7  570.43
   390.7     570   418.6  570.98   426.6  572.09   438.6  572.02  462.03572.8958
  492.07574.6052   510.4  576.14   526.3  578.52   538.2   578.8   558.1  580.28
     574  581.97     582   582.3   605.8  585.21   653.6  587.54   677.4  587.56
#Mann= 7 ,-1 , 0
       0     .12       0    7.88    .016       0   46.86     .12       0
   301.1    .045       0   316.1     .12       0  462.03     .08       0
  492.07     .12       0
#XS Ineff= 2 , 0
           180.6  571.76
Permanent Ineff=
       F       F
Bank Sta=301.1,316.1
XS Rating Curve= 0 ,0
Exp/Cntr=0.3,0.1

Type RM Length L Ch R = 1 ,11258.6 ,163.9,162.1,161.2
XS GIS Cut Line= 3
     2374086.603      290462.305     2374053.846      289989.148
       2374001.5      289806.382
#Sta/Elev= 30
       0   574.1   18.86573.5068   55.98572.8082   195.3  567.82   255.1  567.71
   294.9   569.1   298.9  568.53   302.9  566.76   306.9  564.92   314.9  566.99
   326.8   568.4   366.7  569.15   378.6  570.28   386.6  568.68   390.6  568.82
   410.5  570.85   424.9 571.408   430.4  571.24   446.4  573.11   458.4  573.65
   478.2  576.05  484.34577.3661  510.66579.1027  545.46581.3885   577.3  582.86
  612.69585.4971   636.7  586.77   644.6  586.34   656.5  587.45   664.4  587.13
#Mann= 10 ,-1 , 0
       0     .12       0   18.86    .016       0   55.98     .12       0
   302.9    .045       0   314.9     .12       0   424.9     .06       0
  484.34     .08       0  510.66     .12       0  545.46     .08       0
  612.69     .12       0
#XS Ineff= 2 , 0
                          377.81          570.79
Permanent Ineff=
       F       F
Bank Sta=302.9,314.9
XS Rating Curve= 0 ,0
Exp/Cntr=0.3,0.1

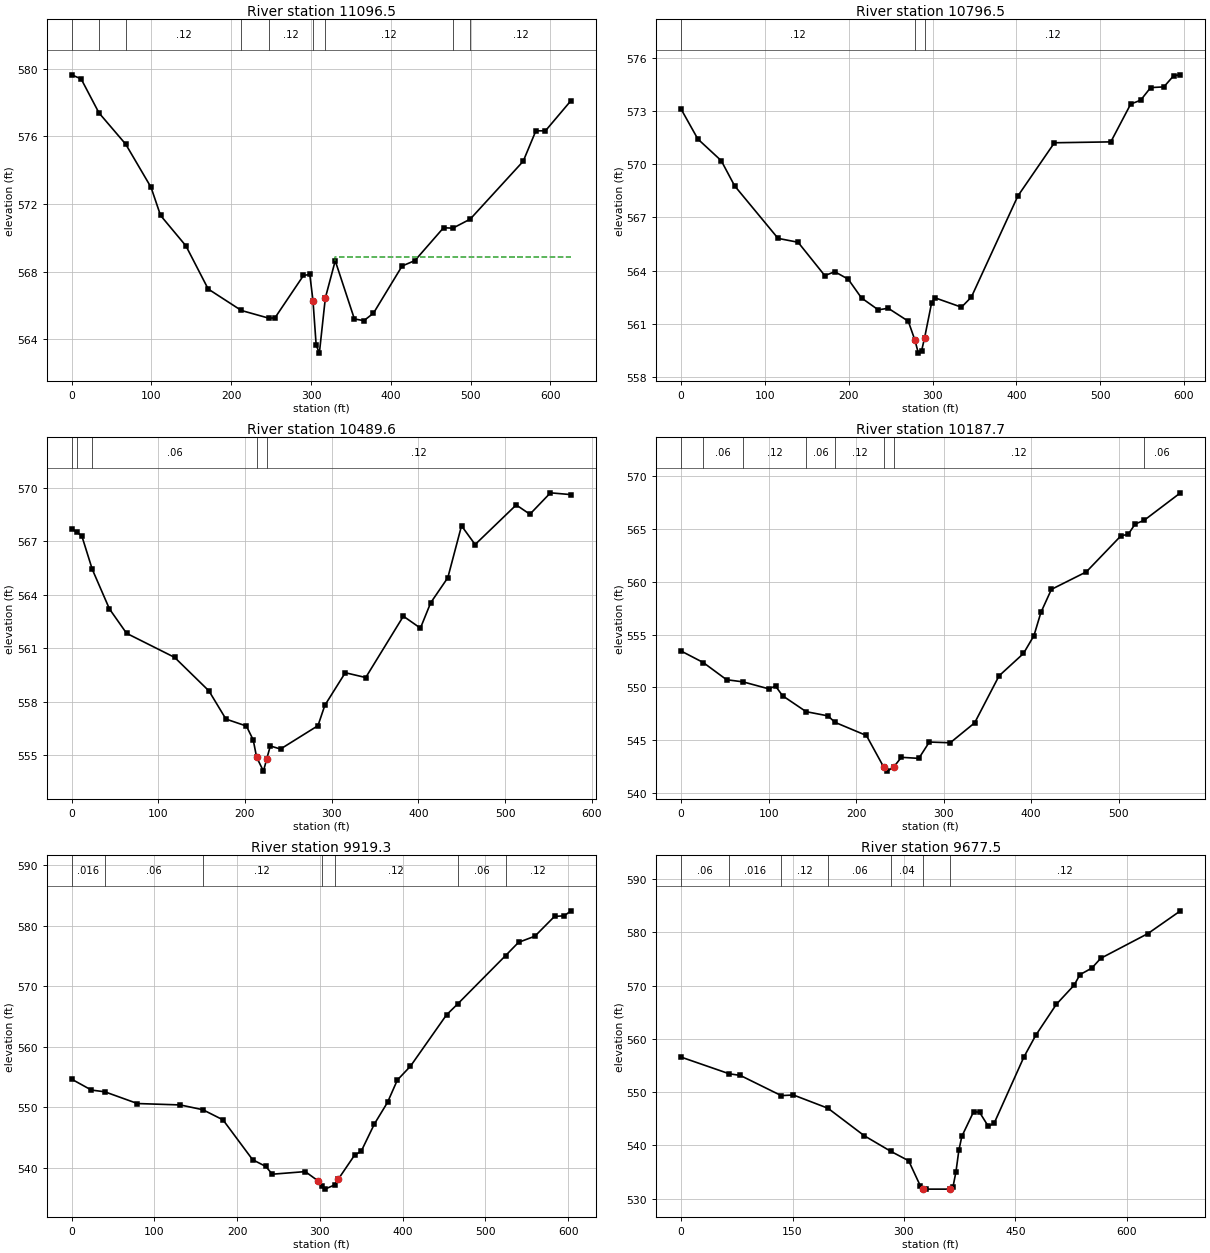
Type RM Length L Ch R = 1 ,11096.5 ,292.5,300,306.5
XS GIS Cut Line= 3
      2374272.38      290440.985     2374225.884      290134.108
     2374192.106      289820.659
#Sta/Elev= 30
       0  579.64    11.9   579.4   34.26577.3893   67.82575.5363    99.5  572.99
   111.4  571.33   143.2  569.53   171.1  566.98  212.66565.7112   246.8565.2595
   254.7  565.27   290.5  567.78   298.4  567.84   302.4   566.3   306.4  563.67
   310.4  563.19   317.9  566.45   330.3  568.65   354.3  565.21   366.2  565.11
   378.2  565.55   414.1  568.34   430.1  568.66     466   570.6  477.68570.5768
  499.41571.1102   565.8  574.53   581.7  576.33   593.7  576.33   625.6  578.11
#Mann= 9 ,-1 , 0
       0     .12       0   34.26    .016       0   67.82     .12       0
  212.66     .06       0   246.8     .12       0   302.4    .045       0
   317.9     .12       0  477.68     .06       0  499.41     .12       0
#XS Ineff= 2 , 0
                          330.13           568.9
Permanent Ineff=
       F       F
Bank Sta=302.4,317.9
XS Rating Curve= 0 ,0
Exp/Cntr=0.3,0.1

Type RM Length L Ch R = 1 ,10796.5 ,314.8,306.9,295.7
XS GIS Cut Line= 3
      2374471.72       290408.61     2374520.807      290129.922
     2374574.146      289821.634
#Sta/Elev= 30
       0   573.1    19.9  571.42    47.8   570.2    63.8  568.78   115.6  565.82
   139.5   565.6   171.4  563.72   183.3  563.94   199.3  563.52   215.2  562.46
   235.2  561.79   247.1  561.88     271  561.15     279  560.07     283  559.35
   286.9  559.48   290.5  560.22   298.8  562.17   302.8  562.47   334.5  561.94
   346.3  562.51   401.8  568.21   445.4  571.21   512.7  571.26   536.4  573.39
   548.3  573.61   560.2  574.32     576  574.36   587.9     575   595.8  575.04
#Mann= 3 ,-1 , 0
       0     .12       0     279    .045       0   290.5     .12       0
Bank Sta=279,290.5
XS Rating Curve= 0 ,0
Exp/Cntr=0.3,0.1

Type RM Length L Ch R = 1 ,10489.6 ,307.4,301.9,295.2
XS GIS Cut Line= 4
     2374754.707      290363.267     2374809.576      290227.354
     2374786.918      290028.063     2374698.582      289816.897
#Sta/Elev= 30
       0   567.7    6.54 567.504    11.9  567.28   23.76565.4352    43.6  563.21
    63.4  561.84   118.8  560.49   158.4  558.61     178  557.03   201.6  556.64
   209.5  555.86   213.4  554.89   221.3  554.11   225.1   554.8   229.2  555.52
     241  555.35   284.2  556.66   292.1   557.8   315.7  559.63   339.3  559.36
   382.7   562.8   402.4  562.13   414.2  563.55     434  564.96   449.8  567.87
   465.5  566.82   512.9  569.04   528.7  568.52   552.4  569.72     576  569.62
#Mann= 5 ,-1 , 0
       0     .06       0    6.54     .12       0   23.76     .06       0
   213.4    .045       0   225.1     .12       0
Bank Sta=213.4,225.1
XS Rating Curve= 0 ,0
Exp/Cntr=0.3,0.1

Type RM Length L Ch R = 1 ,10187.7 ,260.2,268.3,277.6
XS GIS Cut Line= 3
     2375174.174      290309.458     2375091.773      290088.625
     2374968.357      289777.284
#Sta/Elev= 30
       0  553.43   25.22552.3412    51.9  550.71   70.67550.5092    99.9  549.85
   107.9   550.1   115.9  549.19  142.79547.6808   167.8  547.28  175.68546.6729
   211.7  545.42   231.7  542.39   235.7  542.04   243.2  542.46   251.6  543.35
   271.6  543.25   283.6   544.8   307.5  544.73   335.4  546.62   363.3  551.08
   391.2   553.2   403.2   554.9   411.1  557.09   423.1  559.28     463  560.94
   502.8  564.38   510.8  564.49   518.8  565.48  529.06  565.83   570.6  568.44
#Mann= 8 ,-1 , 0
       0     .12       0   25.22     .06       0   70.67     .12       0
  142.79     .06       0  175.68     .12       0   231.7    .045       0
   243.2     .12       0  529.06     .06       0
Bank Sta=231.7,243.2
XS Rating Curve= 0 ,0
Exp/Cntr=0.3,0.1

Type RM Length L Ch R = 1 ,9919.3  ,237.8,241.8,244
XS GIS Cut Line= 3
      2375326.45      290289.923     2375318.752      289900.362
     2375370.049      289692.917
#Sta/Elev= 30
       0  554.67    23.9  552.87   40.06552.5873    79.5  550.65   131.2  550.42
  158.49549.6339   182.9  547.96   218.7  541.39   234.6  540.28   242.5     539
   282.3  539.43   298.2  537.86   302.2  537.02   306.1  536.54   318.1  537.25
     322  538.14   341.9  542.14   349.9  542.78   365.8  547.27   381.7  550.84
   393.6  554.53   409.4   556.8     453  565.27   466.3567.0413   524.4575.0449
     540  577.22   559.8  578.24   583.5   581.5   595.4   581.6   603.3  582.42
#Mann= 7 ,-1 , 0
       0    .016       0   40.06     .06       0  158.49     .12       0
   302.2    .045       0   318.1     .12       0   466.3     .06       0
   524.4     .12       0
Bank Sta=298.2,322
XS Rating Curve= 0 ,0
Exp/Cntr=0.3,0.1

Type RM Length L Ch R = 1 ,9677.5  ,407.5,398.4,390.5
XS GIS Cut Line= 2
     2375486.418      290353.819     2375602.698      289691.664
#Sta/Elev= 30
       0  556.56   64.72553.4348    79.6  553.13  134.73549.3397   151.2  549.45
  197.66546.9654   246.6   541.8  282.68538.8446   306.3  537.11   322.2  532.34
   326.2  531.79   330.2  531.78     362  531.78     366  532.19     370  535.03
   373.9  539.04   377.9  541.68   393.8  546.32   401.8  546.21   413.7  543.54
   421.7  544.23   461.4  556.56   477.4  560.65   505.2  566.48   529.1  570.07
     537  572.05     553  573.28   564.9  575.11   628.5  579.76   672.3  584.03
#Mann= 7 ,-1 , 0
       0     .06       0   64.72    .016       0  134.73     .12       0
  197.66     .06       0  282.68     .04       0   326.2    .045       0
     362     .12       0
Bank Sta=326.2,362
XS Rating Curve= 0 ,0
Exp/Cntr=0.3,0.1

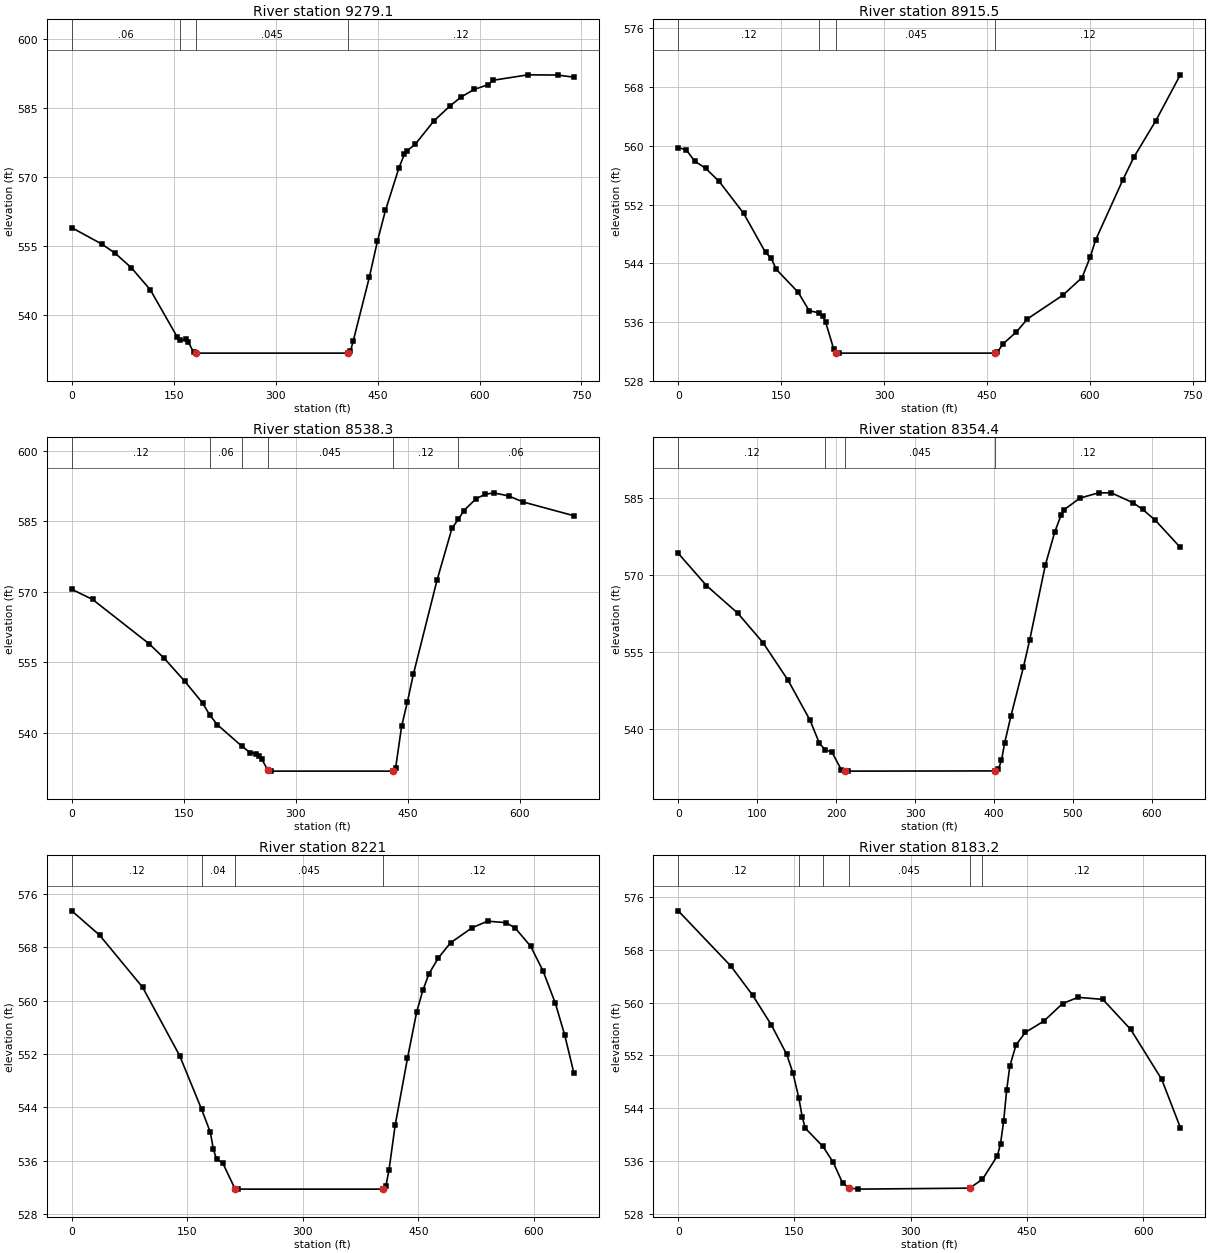
Type RM Length L Ch R = 1 ,9279.1  ,370,363.6,356
XS GIS Cut Line= 3
     2376025.479      290389.277     2375942.594        290032.2
     2375876.841       289665.81
#Sta/Elev= 30
       0  559.01    43.8  555.49    63.8  553.47    87.7  550.31   115.6  545.52
   155.4  535.22  159.91534.5649   167.4  534.75   171.3  534.19   179.3     532
   183.3  531.78   406.2  531.78   410.1   532.2   414.1  534.39   437.8   548.2
   449.7  556.04   461.6  562.76   481.4  571.98   489.3  574.91   493.3  575.72
   505.2  577.08   532.9   582.2   556.6  585.44   572.5  587.34   592.3  589.05
   612.1  590.02     620  591.02   671.5   592.2     715  592.15   738.8  591.69
#Mann= 4 ,-1 , 0
       0     .06       0  159.91     .04       0   183.3    .045       0
   406.2     .12       0
Bank Sta=183.3,406.2
XS Rating Curve= 0 ,0
Exp/Cntr=0.3,0.1

Type RM Length L Ch R = 1 ,8915.5  ,374.8,377.2,379.6
XS GIS Cut Line= 3
     2376477.959      290250.962     2376277.003      289894.161
     2376118.847      289613.355
#Sta/Elev= 30
       0  559.76    11.9  559.42    23.8  557.92    39.8  556.94    59.6  555.15
    95.4  550.79   127.2  545.48   135.2  544.73   143.1  543.16   174.9  540.05
   190.8  537.55  205.37537.2566   210.7   536.8   214.7  536.03   226.6  532.35
   230.6  531.83   234.6  531.78   461.2  531.78   465.2   531.9   473.2  533.02
     493  534.67     509  536.44   560.7  539.67   588.6  542.06   600.5  544.86
   608.4  547.19   648.2  555.39   664.1  558.44     696  563.39   731.8  569.65
#Mann= 4 ,-1 , 0
       0     .12       0  205.37     .04       0   230.6    .045       0
   461.2     .12       0
Bank Sta=230.6,461.2
XS Rating Curve= 0 ,0
Exp/Cntr=0.3,0.1

Type RM Length L Ch R = 1 ,8538.3  ,182.2,183.9,185.7
XS GIS Cut Line= 2
     2376765.242      290084.191     2376499.829       289466.02
#Sta/Elev= 30
       0  570.54    27.9  568.37   103.5  558.94   123.4  555.91   151.3  550.95
   175.2  546.31  184.94 543.729   195.1  541.66  228.24537.0492   238.8  535.74
   246.8  535.53   250.8  535.09   254.8  534.29   262.7  531.95   266.7  531.78
   429.9  531.78   433.9   532.4   441.9  541.32   449.8  546.61   457.8   552.5
   489.6  572.61   509.5  583.58  517.86585.4254   525.4  587.32   541.4   589.8
   553.3  590.75   565.3   591.1   585.2  590.44   605.1  589.13   672.7  586.22
#Mann= 6 ,-1 , 0
       0     .12       0  184.94     .06       0  228.24     .04       0
   262.7    .045       0   429.9     .12       0  517.86     .06       0
Bank Sta=262.7,429.9
XS Rating Curve= 0 ,0
Exp/Cntr=0.3,0.1

Type RM Length L Ch R = 1 ,8354.4  ,133.9,133.4,132.8
XS GIS Cut Line= 2
     2376901.152      290012.182     2376697.256      289409.497
#Sta/Elev= 30
       0  574.18    35.8   567.9    75.6   562.5   107.4  556.79   139.2  549.46
     167  541.69   178.9  537.19  185.99535.9788   194.8  535.48   206.8  531.99
   210.8  531.79   214.7  531.78   401.6  531.82   405.6  532.16   409.6  533.88
   413.6  537.26   421.5  542.47   437.4  552.04   445.4  557.35   465.2  571.92
   477.2  578.38   485.1  581.61   489.1  582.68     509  584.94   532.8  585.96
   548.8  585.96   576.6     584   588.5  582.73   604.4  580.64   636.2  575.33
#Mann= 4 ,-1 , 0
       0     .12       0  185.99     .04       0   210.8    .045       0
   401.6     .12       0
Bank Sta=210.8,401.6
XS Rating Curve= 0 ,0
Exp/Cntr=0.3,0.1

Type RM Length L Ch R = 1 ,8221    ,37.4,37.9,38.3
XS GIS Cut Line= 2
     2377033.852      289973.474     2376807.685      289362.229
#Sta/Elev= 30
       0  573.44      36  569.81      92  561.99     140  551.77  168.52543.7393
   179.9  540.28   183.9  537.72   187.9  536.28   195.9  535.71   211.9  531.83
   215.9  531.78   403.8  531.78   407.8  532.28   411.8  534.61   419.8  541.32
   435.8  551.35   447.8  558.32   455.8  561.54   463.8  564.03   475.8  566.38
   491.8  568.66   519.8  570.91   539.8  571.89   563.8  571.67   575.8  570.85
   595.8  568.12   611.8  564.45   627.8   559.6   639.8   554.9   651.8  549.19
#Mann= 4 ,-1 , 0
       0     .12       0  168.52     .04       0   211.9    .045       0
   403.8     .12       0
Bank Sta=211.9,403.8
XS Rating Curve= 0 ,0
Exp/Cntr=0.3,0.1

Type RM Length L Ch R = 1 ,8183.2  ,212.8,212.9,213
XS GIS Cut Line= 2
     2377063.299      289959.552     2376850.102      289347.725
#Sta/Elev= 30
       0  573.89      68  565.52      96  561.12     120  556.66     140  552.16
     148  549.36  155.61 545.574     160   542.7     164  540.99  186.69538.2407
     200  535.84     212  532.72     220  531.99     232  531.78     376  531.93
  392.59533.2614   411.9  536.84   415.9  538.66   419.9  542.03   423.9  546.84
   427.9   550.4   435.9   553.6   447.9  555.49   471.9  557.21   495.9  559.85
   515.9   560.8   547.9  560.49   583.9  555.94   623.9  548.39   647.9   541.1
#Mann= 6 ,-1 , 0
       0     .12       0  155.61     .06       0  186.69     .04       0
     220    .045       0     376     .08       0  392.59     .12       0
Bank Sta=220,376
XS Rating Curve= 0 ,0
Exp/Cntr=0.3,0.1

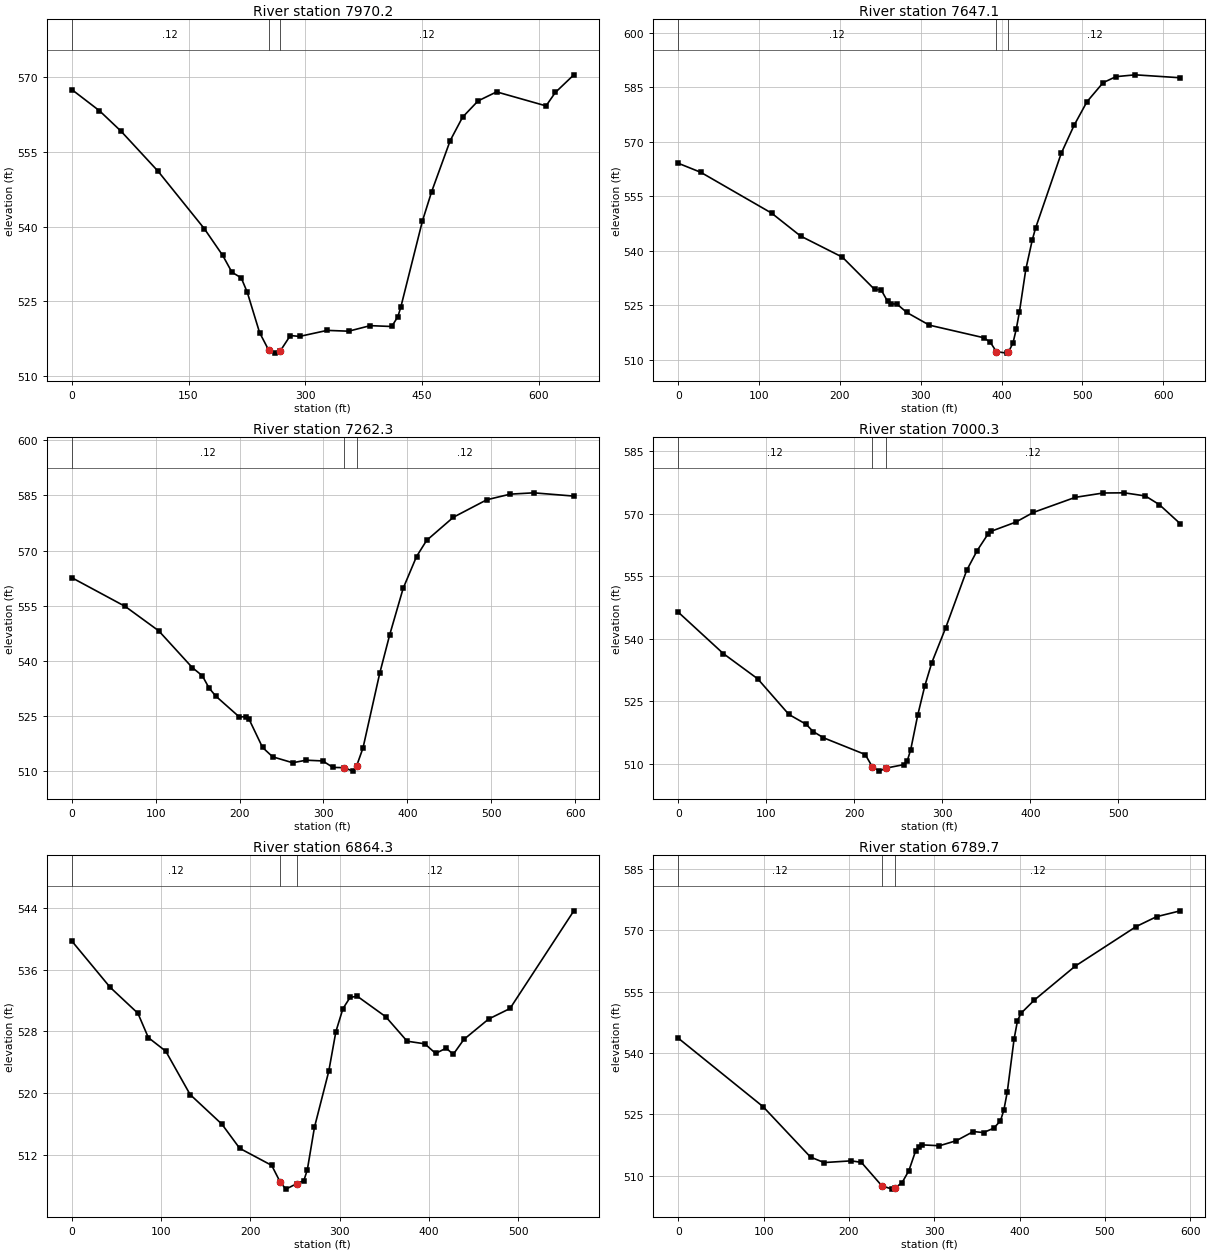
Type RM Length L Ch R = 1 ,7970.2  ,316.9,323.1,329.2
XS GIS Cut Line= 4
     2377211.275      289888.292     2377200.204       289706.59
     2377112.676       289452.98     2377122.395      289258.778
#Sta/Elev= 30
       0  567.48    35.6  563.22    63.3  559.12   110.8   551.1   170.2  539.58
   193.9   534.2   205.7  530.84   217.6  529.72   225.4  526.82   241.2  518.74
   252.7  515.28     261  514.62   267.7  515.04   280.7  518.15   292.5  517.97
     328  519.18   355.6  519.02   383.3  520.13   410.9  519.96   418.8  521.93
   422.7  523.92   450.3   541.1   462.2  547.01     486  557.24   501.9  561.94
   521.8   565.2   545.6  567.01   609.1   564.2     621  566.89   644.8  570.43
#Mann= 3 ,-1 , 0
       0     .12       0   252.7    .045       0   267.7     .12       0
Bank Sta=252.7,267.7
XS Rating Curve= 0 ,0
Exp/Cntr=0.3,0.1

Type RM Length L Ch R = 1 ,7647.1  ,387.4,384.8,391
XS GIS Cut Line= 3
     2377500.267      289783.294     2377393.823      289529.946
     2377370.844      289184.423
#Sta/Elev= 30
       0  564.06    27.9  561.57   115.5  550.34   151.3  544.04   203.1  538.22
   242.9  529.34   250.9  529.27   258.9   526.1   262.8  525.41   270.8  525.28
   282.8     523   310.6  519.52   378.3  516.04   386.2  514.76   393.5  512.24
   406.2  511.82   408.5  512.11   414.1  514.61   418.1  518.37   422.1  523.19
     430  534.92     438  542.98     442   546.2   473.8  566.79   489.7   574.5
   505.7  581.01   525.6  586.23   541.5  587.89   565.4  588.39   621.1  587.58
#Mann= 3 ,-1 , 0
       0     .12       0   393.5    .045       0   408.5     .12       0
Bank Sta=393.5,408.5
XS Rating Curve= 0 ,0
Exp/Cntr=0.3,0.1

Type RM Length L Ch R = 1 ,7262.3  ,254.6,262,260
XS GIS Cut Line= 2
     2377679.117      289745.104     2377801.701      289159.344
#Sta/Elev= 30
       0  562.64    63.8  554.81   103.7  548.18   143.6  538.21   155.6  535.98
   163.6  532.66   171.6  530.46   199.5  524.82   207.5  524.82   211.4  524.12
   227.4  516.49   239.4  513.95   263.3  512.34   279.3  513.03   299.2  512.83
   311.2  511.07   324.4     511   335.1  510.06   339.4  511.41   347.1  516.36
     367  536.62     379  547.17     395  559.76   410.9  568.38   422.9  572.76
   454.8  579.06   494.7  583.82   522.6  585.34   550.6   585.7   598.4  584.81
#Mann= 3 ,-1 , 0
       0     .12       0   324.4    .045       0   339.4     .12       0
Bank Sta=324.4,339.4
XS Rating Curve= 0 ,0
Exp/Cntr=0.3,0.1

Type RM Length L Ch R = 1 ,7000.3  ,136.5,136,133.9
XS GIS Cut Line= 3
       2377894.1      289702.812     2377969.082      289529.849
     2377978.315       289148.14
#Sta/Elev= 30
       0  546.39    51.1  536.48    90.3  530.41   125.7  521.88   145.3  519.52
   153.2  517.79     165  516.29   212.4  512.28   220.3  509.39   228.3   508.3
   236.2  509.03   256.1  509.85   260.1  510.73   264.1  513.47     272  521.69
     280  528.66     288  534.28   303.9   542.7   327.7  556.43   339.6  561.16
   351.6  565.02   355.6  565.78   383.4  567.96   403.3  570.28     451   573.9
   482.8  574.94   506.7  574.98   530.6  574.23   546.5  572.15   570.3  567.56
#Mann= 3 ,-1 , 0
       0     .12       0   220.3    .045       0   236.2     .12       0
Bank Sta=220.3,236.2
XS Rating Curve= 0 ,0
Exp/Cntr=0.3,0.1

Type RM Length L Ch R = 1 ,6864.3  ,75.5,74.6,73.9
XS GIS Cut Line= 4
     2378038.228      289689.977     2378087.278      289550.125
     2378083.992      289306.695     2378105.002      289137.171
#Sta/Elev= 30
       0   539.7    42.9  533.72    74.1  530.35    85.8   527.2   105.3  525.45
   132.6  519.84   168.2  516.01   188.1  512.89     224  510.68  233.69  508.48
     240  507.61     252  508.32     260  508.71   263.9  510.11   271.9  515.61
   287.9  522.84   295.9  527.98   303.8  530.95   311.8   532.4   319.8  532.56
   351.8   529.9   375.7  526.74   395.6   526.4   407.6  525.16   419.5  525.84
   427.4  525.04   439.3  526.97   467.1  529.61     491  530.97   562.5   543.6
#Mann= 3 ,-1 , 0
       0     .12       0  233.69    .045       0     252     .12       0
Bank Sta=233.69,252
XS Rating Curve= 0 ,0
Exp/Cntr=0.3,0.1

Type RM Length L Ch R = 1 ,6789.7  ,191,190.5,189.7
XS GIS Cut Line= 3
     2378159.328      289679.193     2378154.285      289305.592
     2378263.703      289120.857
#Sta/Elev= 30
       0  543.61    99.4  526.87     155  514.55   170.9  513.21   202.7  513.63
   214.6  513.26   238.5  507.55   250.4  506.72   254.4  507.06   262.3  508.31
   270.3  511.26   278.2  516.09   282.2   517.1   286.2  517.53   306.1  517.32
   325.9  518.56   345.8  520.79   357.7  520.54   369.7  521.61   377.6  523.42
   381.6   526.1   385.6  530.54   393.5  543.35   397.5  547.86   401.5  549.66
   417.4  552.94   465.1   561.2   536.6  570.88   560.5  573.29   588.3  574.72
#Mann= 3 ,-1 , 0
       0     .12       0   238.5    .045       0   254.4     .12       0
Bank Sta=238.5,254.4
XS Rating Curve= 0 ,0
Exp/Cntr=0.3,0.1

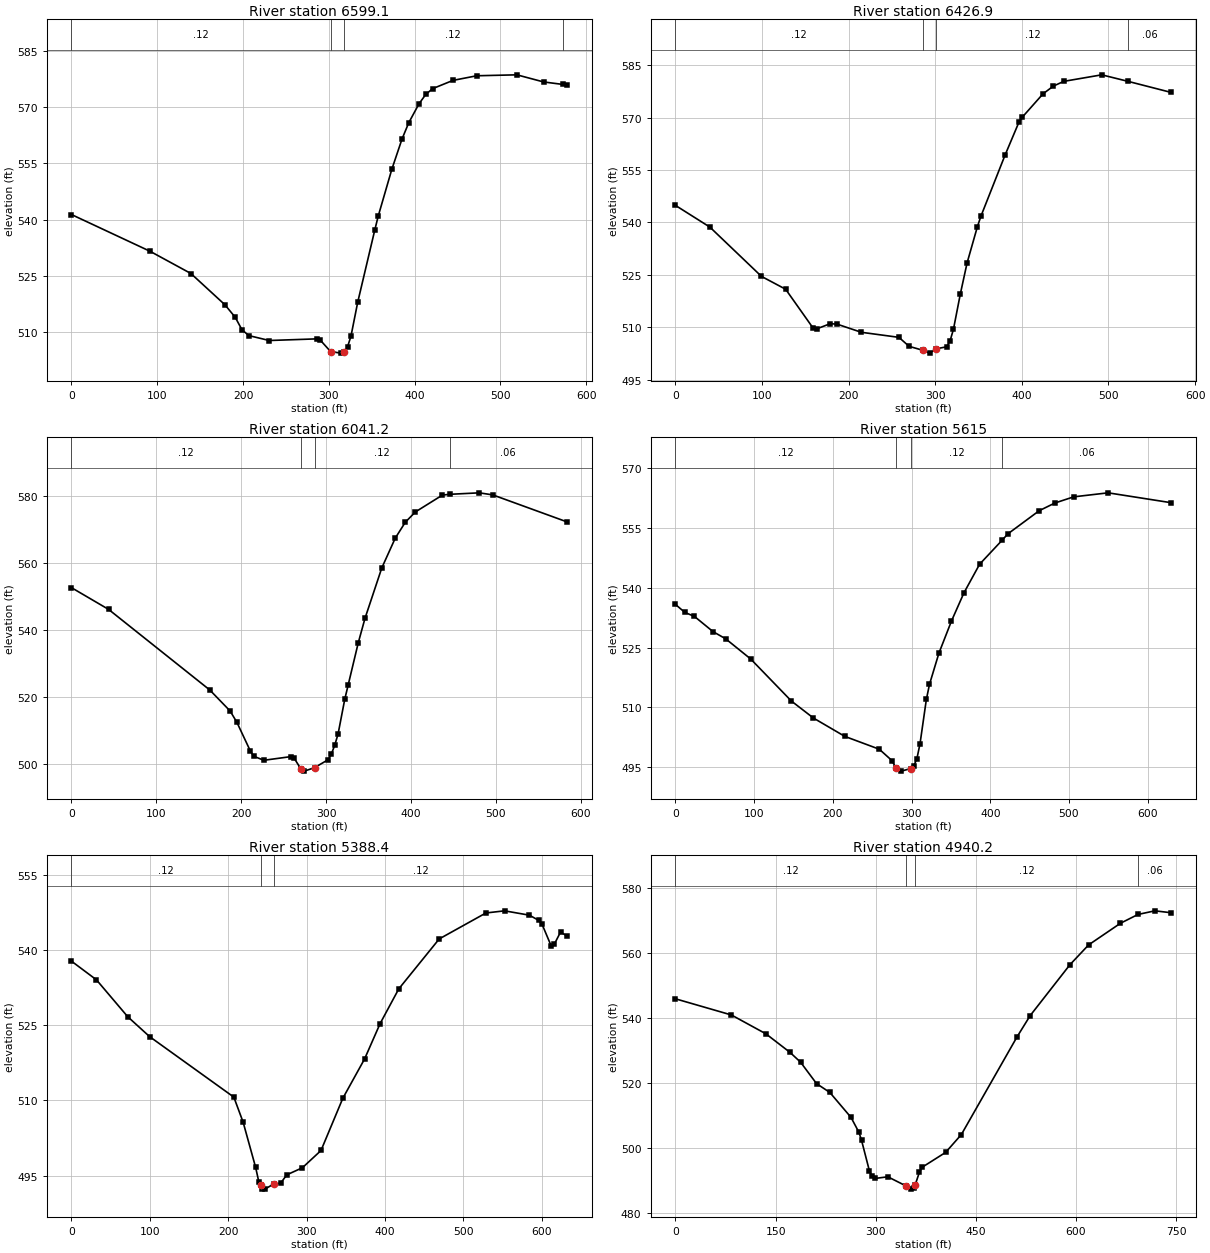
Type RM Length L Ch R = 1 ,6599.1  ,166.1,172.3,178.5
XS GIS Cut Line= 4
     2378276.198      289668.785     2378319.369      289532.165
     2378314.079      289195.018     2378354.855      289107.055
#Sta/Elev= 30
       0  541.33    91.5  531.53   139.3  525.57     179  517.21   190.9  513.89
   198.8  510.55   206.8     509   230.6  507.69   286.1  508.13     290  507.81
     302  504.75   313.9  504.32   317.8  504.52   321.8  505.99   325.8  508.83
   333.7  517.94   353.5  537.12   357.5  540.84   373.4  553.38   385.3  561.48
   393.2  565.85   405.1  570.89     413   573.4     421  574.94   444.8  577.15
   472.5  578.38   519.2  578.63   550.3  576.73  572.42576.0768   577.4  575.86
#Mann= 4 ,-1 , 0
       0     .12       0     302    .045       0   317.8     .12       0
  572.42     .06       0
Bank Sta=302,317.8
XS Rating Curve= 0 ,0
Exp/Cntr=0.3,0.1

Type RM Length L Ch R = 1 ,6426.9  ,392.6,385.7,379.2
XS GIS Cut Line= 4
     2378528.675      289646.301      2378468.86       289431.96
     2378499.931      289313.889     2378488.969      289086.746
#Sta/Elev= 30
       0  544.89    39.7  538.68    99.3  524.56   127.2  520.88     159  509.72
   162.9  509.51   178.8  511.02   186.8  510.86   214.6  508.55     258   507.1
   269.8  504.52   285.6   503.4   293.4  502.58   301.3  503.83   313.1  504.39
     317  506.03     321  509.45   328.9   519.5   336.7   528.4   348.6  538.78
   352.6  541.74   380.5  559.26   396.5  568.68   400.5  570.17   424.4  576.85
   436.4  579.07   448.4  580.42   492.2  582.29  522.94580.3956     572  577.27
#Mann= 4 ,-1 , 0
       0     .12       0   285.6    .045       0   301.3     .12       0
  522.94     .06       0
Bank Sta=285.6,301.3
XS Rating Curve= 0 ,0
Exp/Cntr=0.3,0.1

Type RM Length L Ch R = 1 ,6041.2  ,424.2,426.2,427.2
XS GIS Cut Line= 3
     2378830.571      289619.847     2378821.758      289337.602
     2378821.514      289036.389
#Sta/Elev= 30
       0  552.53    43.8  546.03   163.1  521.94   186.9   515.7   194.9  512.32
   210.8  503.73   214.8  502.17   226.7  500.97   258.5  502.06   262.5  501.55
   270.4  498.35   274.4  497.73   286.4  498.77   302.2  501.11   306.2  502.81
   310.1  505.41   314.1  508.79     322  519.19     326  523.44   337.9  536.05
   345.8  543.33   365.6   558.4   381.5  567.32   393.4  572.09   405.2  575.14
     437  580.17  445.41580.4034   480.6  580.85   496.4  580.23   583.6  572.19
#Mann= 4 ,-1 , 0
       0     .12       0   270.4    .045       0   286.4     .12       0
  445.41     .06       0
Bank Sta=270.4,286.4
XS Rating Curve= 0 ,0
Exp/Cntr=0.3,0.1

Type RM Length L Ch R = 1 ,5615    ,235.2,226.6,218
XS GIS Cut Line= 3
     2379230.219      289593.349     2379248.172      289199.252
     2379126.053      288998.527
#Sta/Elev= 30
       0  535.85      12  533.83    23.9  532.87    47.8  529.01    63.8  527.22
    95.6  522.15   147.4  511.58   175.3  507.33   215.2  502.72     259   499.5
     275  496.66  280.55  494.67   286.9     494   298.9  494.64   302.8   495.3
   306.8  497.12   310.8  500.93   318.8  511.99   322.8  515.79   334.7  523.58
   350.7  531.68   366.6  538.77   386.5  545.95  415.03551.9575   422.4  553.57
   462.2  559.38   482.1  561.31     506  562.86   549.8  563.87   629.5   561.4
#Mann= 4 ,-1 , 0
       0     .12       0  280.55    .045       0   298.9     .12       0
  415.03     .06       0
Bank Sta=280.55,298.9
XS Rating Curve= 0 ,0
Exp/Cntr=0.3,0.1

Type RM Length L Ch R = 1 ,5388.4  ,446.6,448.2,439.6
XS GIS Cut Line= 3
      2379437.36      289578.059     2379478.672      289395.283
     2379336.821      288973.953
#Sta/Elev= 30
       0   537.8    31.9  534.07    71.8  526.71    99.7  522.74   207.2  510.66
   219.1  505.63     235  496.64     239   493.8  241.38  493.07     243  492.42
   246.9   492.3   258.8   493.4   266.8  493.46   274.7  495.15   294.6  496.56
   318.4  500.01   346.2  510.42     374  518.28   393.8  525.34   417.6  532.26
   469.2  542.23   528.8  547.41   552.6  547.84   584.3  546.97   596.2  545.93
   600.2  545.24   612.1  540.82   616.1   541.2     624   543.6     632  542.84
#Mann= 3 ,-1 , 0
       0     .12       0  241.38    .045       0   258.8     .12       0
Bank Sta=241.38,258.8
XS Rating Curve= 0 ,0
Exp/Cntr=0.3,0.1

Type RM Length L Ch R = 1 ,4940.2  ,328.7,338.4,347.9
XS GIS Cut Line= 4
     2379815.224      289482.517      2379777.61      289234.106
     2379688.478      289067.514     2379775.165      288778.097
#Sta/Elev= 30
       0  545.88    83.8   540.9   135.6  535.08   171.5  529.39   187.4  526.36
   211.4  519.74   231.3  517.02     263  509.34   274.9  504.73   278.8  502.28
   290.6  492.85   294.5  491.18   298.5   490.5   318.2  491.02   345.7  488.18
   353.6  487.22   357.5   487.6  359.07  488.45   365.4  492.36   369.3  493.92
   404.8  498.54   428.4  504.05   511.7  534.11   531.6  540.73   591.2  556.42
   619.1   562.5   666.8  569.17  693.12571.8853   718.4     573   742.3  572.42
#Mann= 4 ,-1 , 0
       0     .12       0   345.7    .045       0  359.07     .12       0
  693.12     .06       0
Bank Sta=345.7,359.07
XS Rating Curve= 0 ,0
Exp/Cntr=0.3,0.1

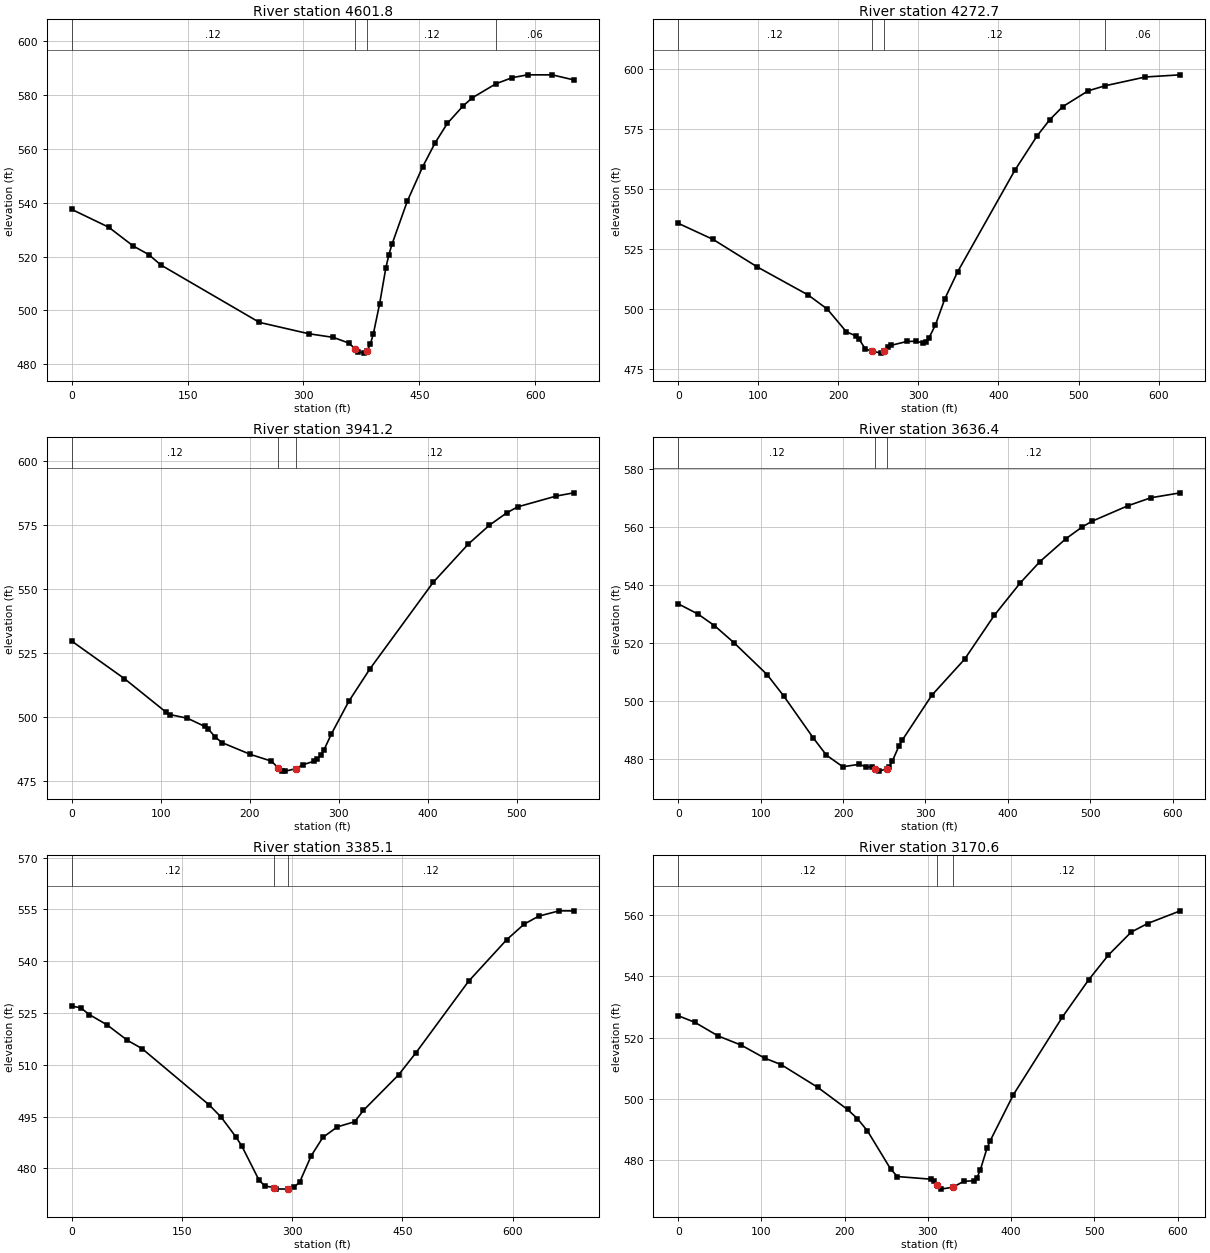
Type RM Length L Ch R = 1 ,4601.8  ,329.3,329.1,327.4
XS GIS Cut Line= 3
     2380100.699      289341.796     2380010.272      289086.604
      2379971.15      288709.334
#Sta/Elev= 30
       0  537.44    47.8  530.85    79.6  523.88    99.5  520.74   115.5  516.83
   242.9   495.6   306.7   491.4   338.6  490.04   358.6  487.95   366.6  485.88
   370.6  484.72   378.5  484.21   382.5  485.14   386.5   487.5   390.5  491.43
   398.5  502.42   406.5   515.6   410.5  520.62   414.5  524.49   434.4  540.49
   454.4  553.29   470.4   562.1   486.3  569.33   506.3  575.67   518.3  578.74
  549.14583.9802   570.2  586.24   590.1  587.29   622.1  587.27     650   585.4
#Mann= 4 ,-1 , 0
       0     .12       0   366.6    .045       0   382.5     .12       0
  549.14     .06       0
Bank Sta=366.6,382.5
XS Rating Curve= 0 ,0
Exp/Cntr=0.3,0.1

Type RM Length L Ch R = 1 ,4272.7  ,335.6,331.6,328.6
XS GIS Cut Line= 3
     2380276.707       289284.87     2380322.468      289067.818
      2380269.27      288666.007
#Sta/Elev= 30
       0  535.61    43.6  528.88      99  517.37   162.4  505.71   186.2  499.84
   209.9  490.43   221.8  488.68   225.8  487.35   233.8  483.18   241.7  482.37
   253.6   481.5   257.6  482.36   261.6     484   265.5  484.71   285.4  486.35
   297.3  486.46   305.3  485.78   309.2   486.3   313.2  487.86   321.2  493.21
   333.1  504.23     349  515.42   420.5  557.75   448.3  572.09   464.2  578.85
   480.1   584.2   511.9  590.82  532.86592.9148   583.4   596.6   627.1   597.5
#Mann= 4 ,-1 , 0
       0     .12       0   241.7    .045       0   257.6     .12       0
  532.86     .06       0
Bank Sta=241.7,257.6
XS Rating Curve= 0 ,0
Exp/Cntr=0.3,0.1

Type RM Length L Ch R = 1 ,3941.2  ,303,304.8,306.5
XS GIS Cut Line= 3
     2380708.417      289223.152     2380637.087      288989.662
     2380544.688      288683.103
#Sta/Elev= 30
       0  529.64    59.1  514.97   106.3  501.73   110.3  500.88     130  499.44
   149.6  496.22   153.6   495.2   161.4  491.98   169.3  489.83   200.8  485.28
   224.4  482.64   232.3  479.88   236.3  478.91   240.2  478.73   251.6  479.66
     260  481.26   271.8  482.55   275.8   483.4   279.7  484.98   283.7  487.19
   291.6  493.16   311.3  506.03   335.1  518.77   406.2  552.65   445.7  567.66
   469.4  575.04   489.2  579.95   501.1  582.21   544.6  586.47   564.3  587.72
#Mann= 3 ,-1 , 0
       0     .12       0   232.3    .045       0   251.6     .12       0
Bank Sta=232.3,251.6
XS Rating Curve= 0 ,0
Exp/Cntr=0.3,0.1

Type RM Length L Ch R = 1 ,3636.4  ,252.5,251.2,249.9
XS GIS Cut Line= 3
     2380989.728      289177.263       2380906.9       288806.92
     2380761.907      288628.812
#Sta/Elev= 30
       0  533.63      24  530.09    43.9  526.12    67.9  520.14   107.9  509.18
   127.8  501.91   163.8  487.37   179.8  481.41   199.7  477.41   219.7  478.25
   227.7  477.36   235.7  477.27   238.3  476.76   243.7   475.9   253.3  476.72
   255.7  477.22   259.6  479.25   267.6  484.43   271.6   486.5   307.6  502.05
   347.5  514.53   383.4  529.62   415.1  540.88   438.9  548.21   470.6  556.14
   490.4   560.2   502.2  562.14   545.8  567.49   573.5  570.23   609.2  571.93
#Mann= 3 ,-1 , 0
       0     .12       0   238.3    .045       0   253.3     .12       0
Bank Sta=238.3,253.3
XS Rating Curve= 0 ,0
Exp/Cntr=0.3,0.1

Type RM Length L Ch R = 1 ,3385.1  ,211.3,214.5,217.7
XS GIS Cut Line= 4
     2381170.393      289147.793     2381193.477      288925.685
     2381149.372      288770.131     2380910.526      288591.667
#Sta/Elev= 30
       0  526.98      12  526.55    23.9  524.56    47.8  521.61    75.8  517.09
    95.7   514.7   187.4  498.32   203.4  494.83   223.3  489.15   231.2  486.58
   254.8  476.62   262.7  474.94   274.6  474.48   278.5  474.08   294.3  474.02
   302.2  474.56   310.1  476.04   325.8  483.67   341.6  488.98   361.3  492.04
     385  493.54   396.9  496.83   444.6  507.08   468.5  513.55     540  534.22
   591.7  546.21   615.6  550.75   635.4  553.06   663.3   554.6   683.2  554.57
#Mann= 3 ,-1 , 0
       0     .12       0   274.6    .045       0   294.3     .12       0
Bank Sta=274.6,294.3
XS Rating Curve= 0 ,0
Exp/Cntr=0.3,0.1

Type RM Length L Ch R = 1 ,3170.6  ,206.3,207.4,208.4
XS GIS Cut Line= 3
      2381405.46      289103.648     2381354.622      288716.016
     2381386.241      288506.041
#Sta/Elev= 30
       0  527.17      20  525.01    47.9  520.58    75.8  517.56   103.7  513.36
   123.7  511.21   167.6  503.81   203.4  496.58   215.4  493.56   227.4  489.57
   255.3  477.11   263.3  474.69   303.2  473.83   307.2  473.31   311.2  471.85
   315.2  470.58   329.7  471.17   343.1  473.12     355  473.32     359  474.26
     363  476.87     371  483.91     375  486.44   402.8  501.43   461.7  526.78
   493.2   538.9   516.8  546.94   544.3  554.47     564  557.27   603.3  561.41
#Mann= 3 ,-1 , 0
       0     .12       0   311.2    .045       0   329.7     .12       0
Bank Sta=311.2,329.7
XS Rating Curve= 0 ,0
Exp/Cntr=0.3,0.1