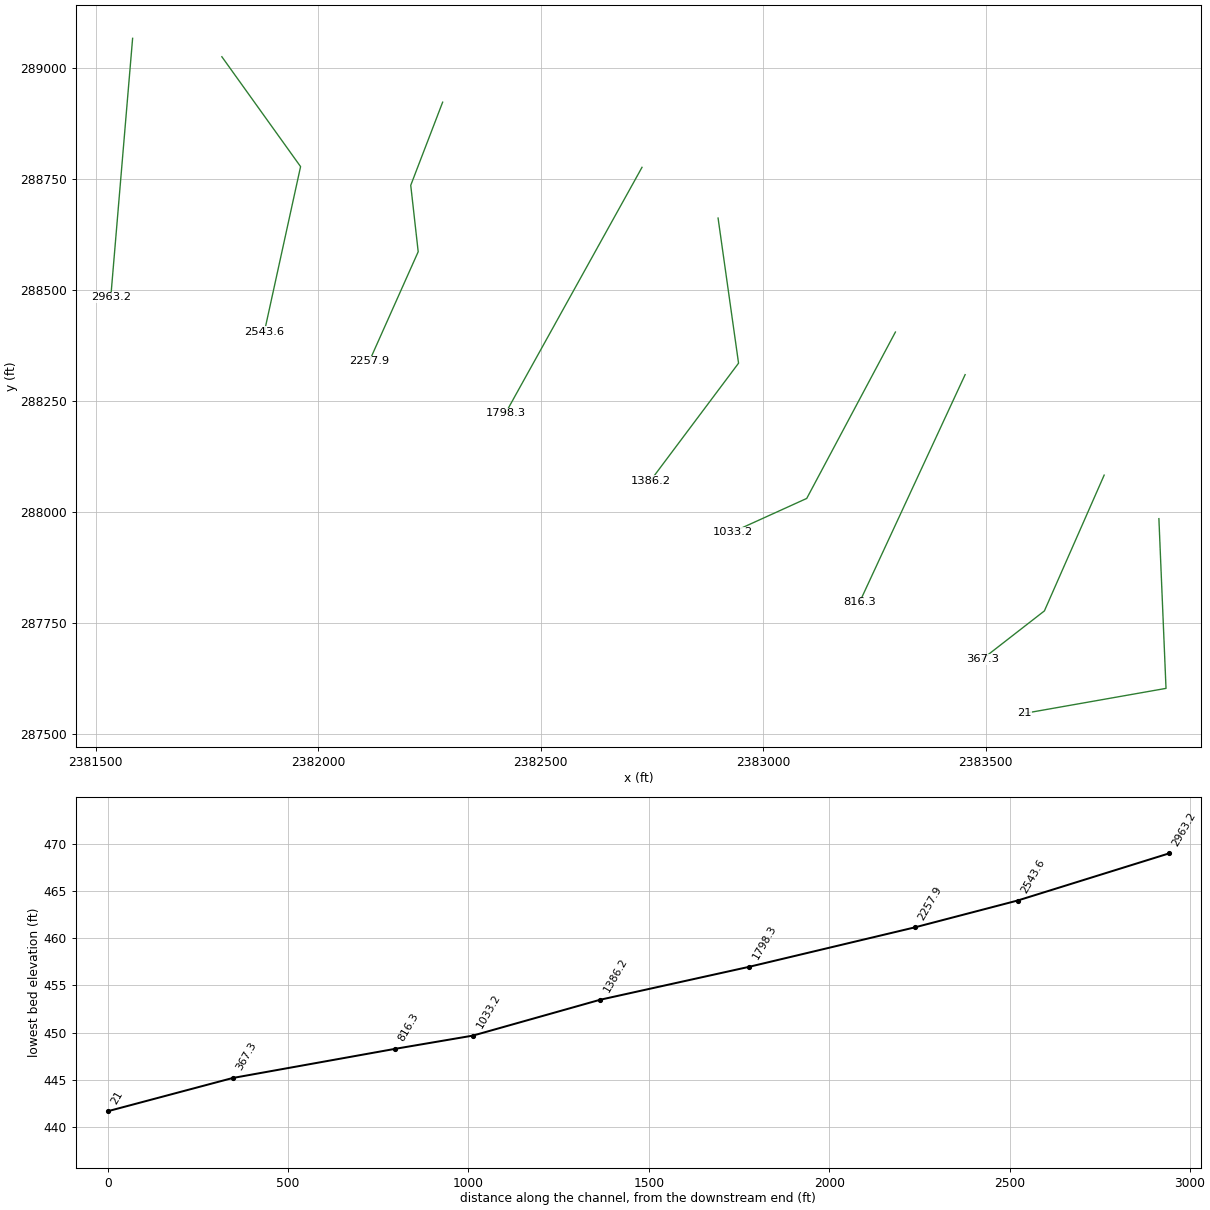
HEC-RAS study DUNCANRUN.prj: DUNCANRUN

--- DUNCANRUN.g01 (geometry) --- (continued)

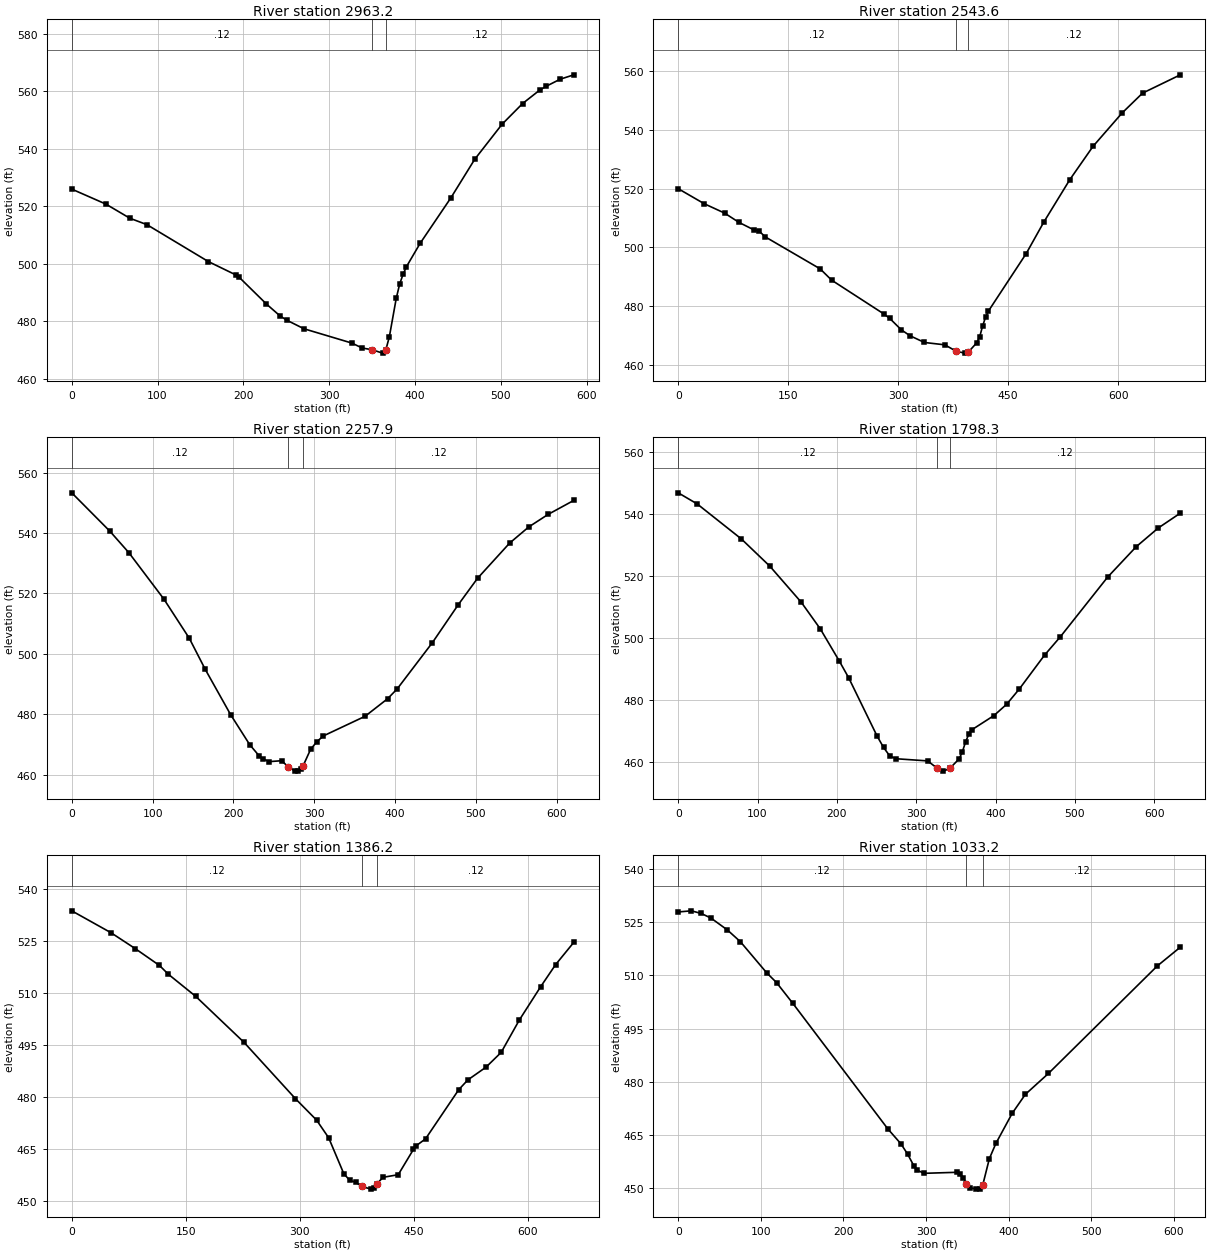
Type RM Length L Ch R = 1 ,2963.2  ,423.8,419.6,415.1
XS GIS Cut Line= 2
     2381582.732      289066.992     2381533.613       288483.89
#Sta/Elev= 30
       0  525.98    39.8  520.77    67.7  515.86    87.6  513.63   159.2   500.8
   191.1  496.18   195.1  495.35   226.9  486.04   242.8   481.9   250.8   480.4
   270.7  477.44   326.4  472.48   338.4  470.77   350.3  470.14   362.2  468.98
   366.2  470.24   370.2  474.73   378.2  488.03   382.2  493.01   386.1  496.33
   390.1  499.03     406  507.12   441.9  522.96   469.7  536.36   501.6  548.55
   525.5  555.73   545.4  560.39   553.3  561.77   569.2  564.17   585.2   565.7
#Mann= 3 ,-1 , 0
       0     .12       0   350.3    .045       0   366.2     .12       0
Bank Sta=350.3,366.2
XS Rating Curve= 0 ,0
Exp/Cntr=0.3,0.1

Type RM Length L Ch R = 1 ,2543.6  ,278.4,285.7,292.9
XS GIS Cut Line= 3
     2381783.314      289025.562      2381960.24      288778.244
     2381878.871      288406.292
#Sta/Elev= 30
       0  520.03    35.5   514.9    63.2  511.72    82.9  508.54   102.7  506.06
   110.6  505.53   118.5  503.64   193.5  492.72   209.3  488.85   280.4  477.35
   288.3  475.87   304.1  471.97     316  469.93   335.8  467.62   363.6  466.82
   379.4  464.59   391.3  463.99   395.3  464.24   407.2  467.53   411.2   469.6
   415.1  473.18   419.1   476.2   423.1  478.33   474.6  497.92   498.4  508.56
   534.1  523.12   565.8  534.48   605.5  545.86   633.3   552.6   684.8  558.84
#Mann= 3 ,-1 , 0
       0     .12       0   379.4    .045       0   395.3     .12       0
Bank Sta=379.4,395.3
XS Rating Curve= 0 ,0
Exp/Cntr=0.3,0.1

Type RM Length L Ch R = 1 ,2257.9  ,474,459.6,443.3
XS GIS Cut Line= 4
     2382279.568      288923.325     2382207.837      288736.167
     2382224.587      288586.602      2382114.59      288339.749
#Sta/Elev= 30
       0   553.3    47.2  540.58    70.7  533.46     114   518.1   145.4  505.14
   165.1  494.86   196.5  479.86   220.2  469.89   232.1  466.11   236.1  465.32
     244  464.28   259.8  464.59   267.8  462.53   275.7  461.22   279.6  461.14
   283.6   461.7   286.3  462.94   295.5  468.36   303.4  470.93   311.3   472.8
   362.9   479.3   390.7   485.1   402.6  488.36   446.3  503.73   478.1  516.22
     502  524.98   541.7  536.64   565.5  542.02   589.4  546.16   621.2   550.8
#Mann= 3 ,-1 , 0
       0     .12       0   267.8    .045       0   286.3     .12       0
Bank Sta=267.8,286.3
XS Rating Curve= 0 ,0
Exp/Cntr=0.3,0.1

Type RM Length L Ch R = 1 ,1798.3  ,414.9,412,409
XS GIS Cut Line= 2
     2382727.601      288776.632     2382420.762      288222.945
#Sta/Elev= 30
       0  546.86    23.9  543.27    79.6  531.96   115.5  523.16   155.3  511.45
   179.2  502.87     203  492.55     215  487.06   250.8  468.24   258.8  464.64
   266.8  461.82   274.7  460.96   314.5  460.26   326.5  457.89   334.4  456.96
   342.4  457.84   354.3  460.97   358.3  463.28   362.3  466.41   366.3  468.88
   370.3  470.34   398.1  474.92     414  478.55     430  483.48   461.8  494.42
   481.7  500.34   541.4  519.64   577.3  529.43   605.2   535.5     633   540.3
#Mann= 3 ,-1 , 0
       0     .12       0   326.5    .045       0   342.4     .12       0
Bank Sta=326.5,342.4
XS Rating Curve= 0 ,0
Exp/Cntr=0.3,0.1

Type RM Length L Ch R = 1 ,1386.2  ,378.5,353,347.7
XS GIS Cut Line= 3
      2382898.56      288662.411      2382944.59      288335.732
     2382746.603      288071.102
#Sta/Elev= 30
       0  533.74    51.7  527.41    83.5  522.84   115.3  517.99   127.2  515.42
     163  509.08   226.6   495.8   294.1  479.58     322  473.39   337.9  468.29
   357.8  457.94   365.7  455.99   373.7  455.46   381.7  454.24   393.6  453.48
   397.6   453.8   401.6  455.08   409.5  456.89   429.4  457.64   449.4  464.93
   453.3  466.04   465.3  467.97   509.1  482.19     521  484.98   544.9  488.66
   564.8  492.91   588.7  502.25   616.6  511.81   636.5  518.25   660.4  524.67
#Mann= 3 ,-1 , 0
       0     .12       0   381.7    .045       0   401.6     .12       0
Bank Sta=381.7,401.6
XS Rating Curve= 0 ,0
Exp/Cntr=0.3,0.1

Type RM Length L Ch R = 1 ,1033.2  ,216.3,216.9,217.3
XS GIS Cut Line= 3
     2383297.113        288405.8     2383097.796      288031.254
     2382930.651      287955.266
#Sta/Elev= 30
       0  527.93    15.9  528.25    27.8  527.51    39.6  526.21    59.5  522.85
    75.3  519.52   107.1  510.75     119     508   138.8  502.11   253.8  466.68
   269.6  462.48   277.6  459.61   285.5  456.17   289.5  455.04   297.4  454.14
     337  454.43     341  454.03     345  452.95   348.9  451.21   352.9   450.1
   360.8  449.68   364.8  449.81   368.8  450.94   376.7  458.29   384.6  462.58
   404.4   471.1   420.3  476.44   448.2  482.33     580  512.68   607.9  517.99
#Mann= 3 ,-1 , 0
       0     .12       0   348.9    .045       0   368.8     .12       0
Bank Sta=348.9,368.8
XS Rating Curve= 0 ,0
Exp/Cntr=0.3,0.1

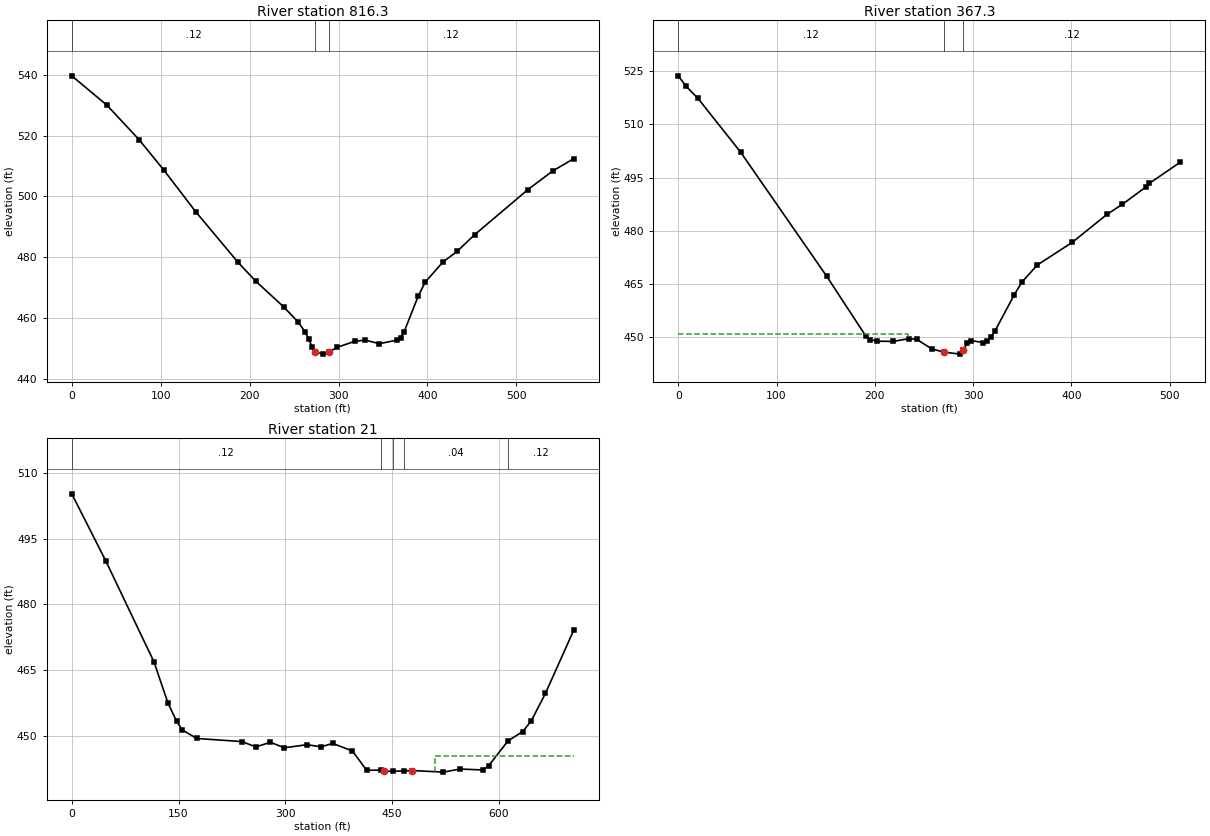
Type RM Length L Ch R = 1 ,816.3   ,443.2,449,448.4
XS GIS Cut Line= 2
     2383453.794      288309.869     2383216.517      287797.474
#Sta/Elev= 30
       0  539.59    39.8  529.89    75.6  518.67   103.4  508.72   139.2  495.07
   186.9  478.42   206.8  472.24   238.6   463.7   254.5  458.83   262.4  455.57
   266.4  453.33   270.4  450.51   273.9  449.07   282.3  448.27   288.9  448.83
   298.2  450.47   318.1  452.46     330  452.87     346   451.7   365.8  452.88
   369.8  453.71   373.8  455.59   389.7  467.33   397.6  471.94   417.5   478.5
   433.4  481.99   453.3   487.5     513  502.25   540.8  508.34   564.7  512.43
#Mann= 3 ,-1 , 0
       0     .12       0   273.9    .045       0   288.9     .12       0
Bank Sta=273.9,288.9
XS Rating Curve= 0 ,0
Exp/Cntr=0.3,0.1

Type RM Length L Ch R = 1 ,367.3   ,372.5,346.3,320.9
XS GIS Cut Line= 3
     2383766.326      288083.758     2383632.005       287778.09
     2383492.385      287669.387
#Sta/Elev= 30
       0  523.72       8  520.75    19.9  517.42    63.6  502.13     151  467.18
   190.8   450.3   194.8   449.3   202.7  448.83   218.6  448.78   234.5  449.54
   242.5  449.37   258.4   446.6   270.3  445.78   286.2  445.19   290.2  446.36
   294.1  448.27   298.1     449     310  448.47     314  448.92     318     450
     322  451.59   341.7  461.87   349.6   465.5   365.3  470.34   400.7  476.69
   436.1   484.6   451.8  487.45   475.4  492.28   479.4  493.39   510.8  499.36
#Mann= 3 ,-1 , 0
       0     .12       0   270.3    .045       0   290.2     .12       0
#XS Ineff= 2 , 0
          234.06  450.81
Permanent Ineff=
       F       F
Bank Sta=270.3,290.2
XS Rating Curve= 0 ,0
Exp/Cntr=0.3,0.1

Type RM Length L Ch R = 1 ,21      ,23,21,19
XS GIS Cut Line= 3
     2383889.311      287985.769     2383905.304      287603.669
     2383587.064      287547.399
#Sta/Elev= 30
       0  505.23    47.8  489.91   115.5  466.86   135.4  457.36   147.4  453.25
   155.4  451.32   175.3  449.36     239  448.65   258.9  447.42   278.9   448.5
   298.8  447.23   330.6  447.94   350.6  447.44   366.5  448.24   394.4   446.5
   414.4   442.1   433.9 442.126   438.3  441.91   451.9  441.86   466.9  441.96
   478.2  442.04   522.1  441.67     546  442.38   577.9  442.16   585.9  443.14
  613.13 448.813   633.8  450.94   645.8  453.38   665.7  459.66   705.6  474.15
#Mann= 5 ,-1 , 0
       0     .12       0   433.9     .04       0   451.9    .045       0
   466.9     .04       0  613.13     .12       0
#XS Ineff= 2 , 0
                          511.04          445.44
Permanent Ineff=
       F       F
Bank Sta=438.3,478.2
XS Rating Curve= 0 ,0
Exp/Cntr=0.3,0.1

Chan Stop Cuts=-1
Use User Specified Reach Order=0
Composite Channel Slope=5